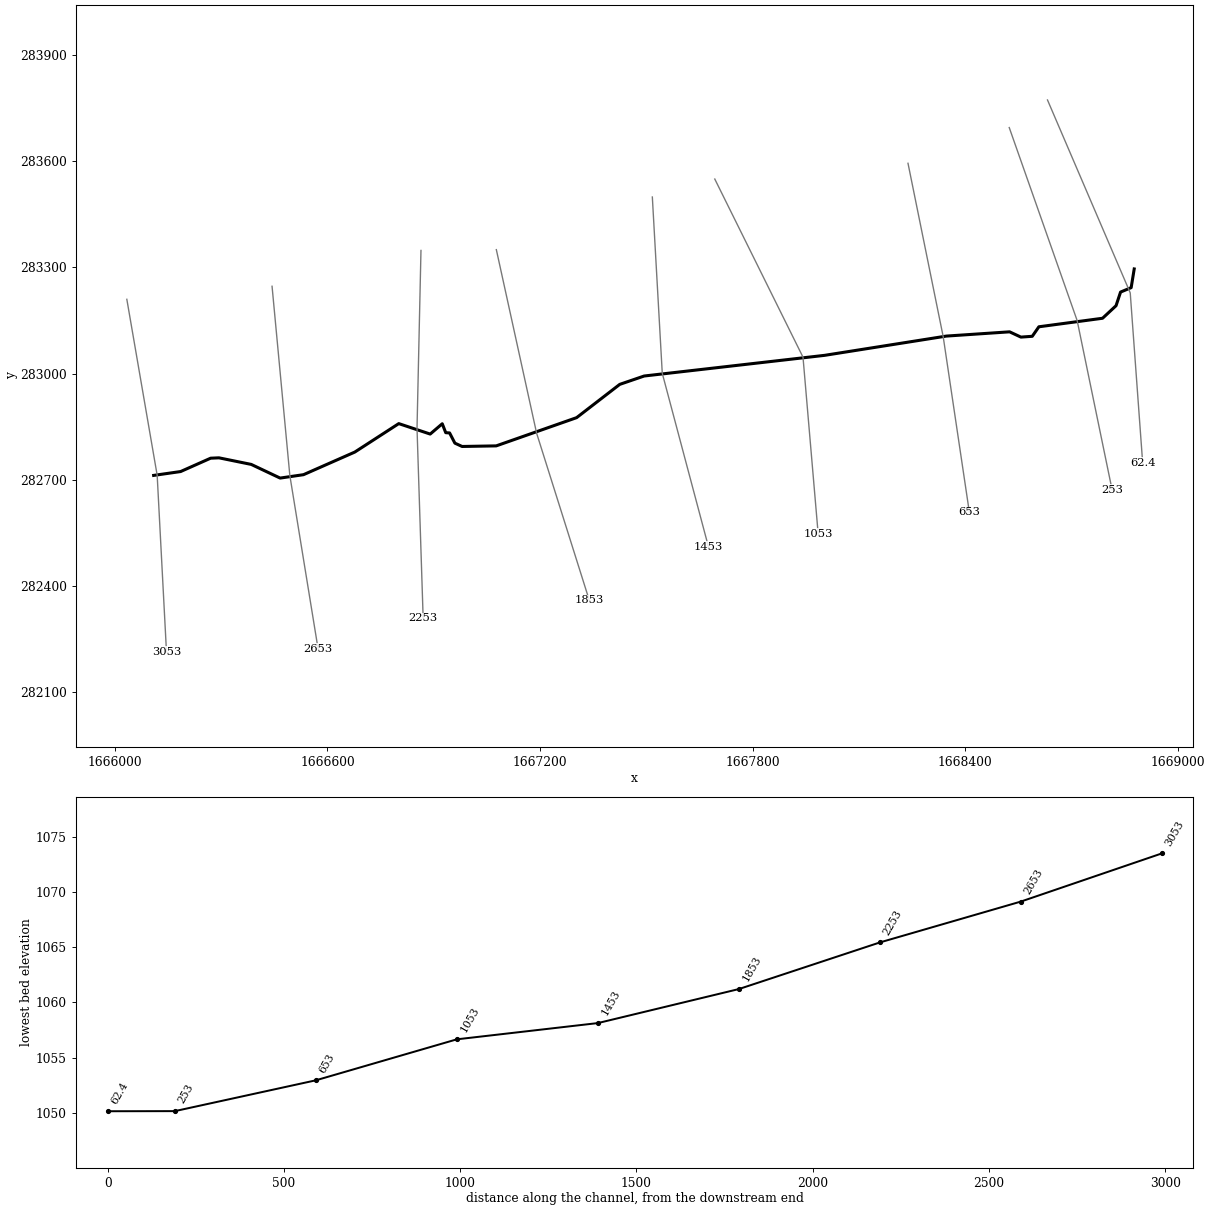
--- PtrsnFkTr.prj (project) ---

Proj Title=PtrsnFkTr
Current Plan=p01
Geom File=g01
Flow File=f01
Plan File=p01
DSS Export Rating Curves=0
DSS Export Rating Curve Sorted=0
DSS Export Volume Flow Curves=0
DXF OffsetX=0
DXF OffsetY=0
DXF ScaleX=0
DXF ScaleY=0

--- PtrsnFkTr.p01 (plan) ---

Plan Title=Floodplain
Program Version=4.00
Geom File=g01
Flow File=f01
K Sum by GR=0
Std Step Tol=0.01
Critical Tol=0.01
Num of Std Step Trials=20
Max Error Tol=0.3
Flow Tol Ratio=0.001
Split Flow NTrial=30
Split Flow Tol=0.02
Split Flow Ratio=0.02
Log Output Level=0
Friction Slope Method=1
Unsteady Friction Slope Method=2
Unsteady Bridges Friction Slope Method=1
Global Log Level=0
CheckData=False
Run HTab=0
Run UNet=0
Run PostProcess=0
UNET Theta=0
UNET Theta Warmup=0
UNET ZTol=0
UNET ZSATol=0
UNET MxIter=0
UNET MaxInSteps=0
UNET DtIC=0
UNET DtMin=0
UNET MaxCRTS=0
UNET WFStab=0
UNET SFStab=0
UNET WFX=0
UNET SFX=0
UNET DSS MLevel=0
UNET DZMax Abort=0
UNET Convert EG Bridges=0
UNET Use Existing IB Tables=0
UNET Froude Limit=0
UNET Froude Power=0
Write IC File=0
Echo Input=False
Echo Output=False
Write Detailed=0

--- PtrsnFkTr.f01 (steady flow) ---

Flow Title=NFF Regression Equation
Program Version=4.00
Number of Profiles=1
Profile Names=P100yr
River Rch & RM=PtrsnFkTr,Main      ,3053
743.2307
River Rch & RM=PtrsnFkTr,Main      ,1853
759.9212
River Rch & RM=PtrsnFkTr,Main      ,253
843.7612
River Rch & RM=PtrsnFkTr,Main      ,62.4
1023.691
Boundary for River Rch & Prof#=PtrsnFkTr,Main      ,1
Up Type=0
Dn Type=3
Dn Slope=0.006502

--- PtrsnFkTr.g01 (geometry) ---

Geom Title=USGS 3m DEM
Program Version=4.00

River Reach=PtrsnFkTr     ,Main
Reach XY= 30
     1666109.619      282711.981     1666185.768      282722.928
     1666270.508      282760.694     1666293.959      282761.705
     1666385.016      282743.089     1666466.529      282704.449
     1666532.451      282714.059     1666677.269      282778.036
     1666801.252      282858.471     1666889.888      282828.905
     1666923.959      282858.070     1666933.769      282832.801
     1666944.658      282832.130     1666959.575      282803.230
     1666979.938      282793.826     1667076.167      282795.506
     1667303.040      282875.339     1667424.733      282969.418
     1667493.614      282993.072     1668002.520      283051.471
     1668346.246      283105.969     1668524.664      283117.997
     1668556.581      283103.080     1668588.638      283105.366
     1668607.253      283132.244     1668786.944      283156.368
     1668824.979      283191.850     1668837.749      283230.422
     1668867.654      283242.922     1668876.255      283295.808

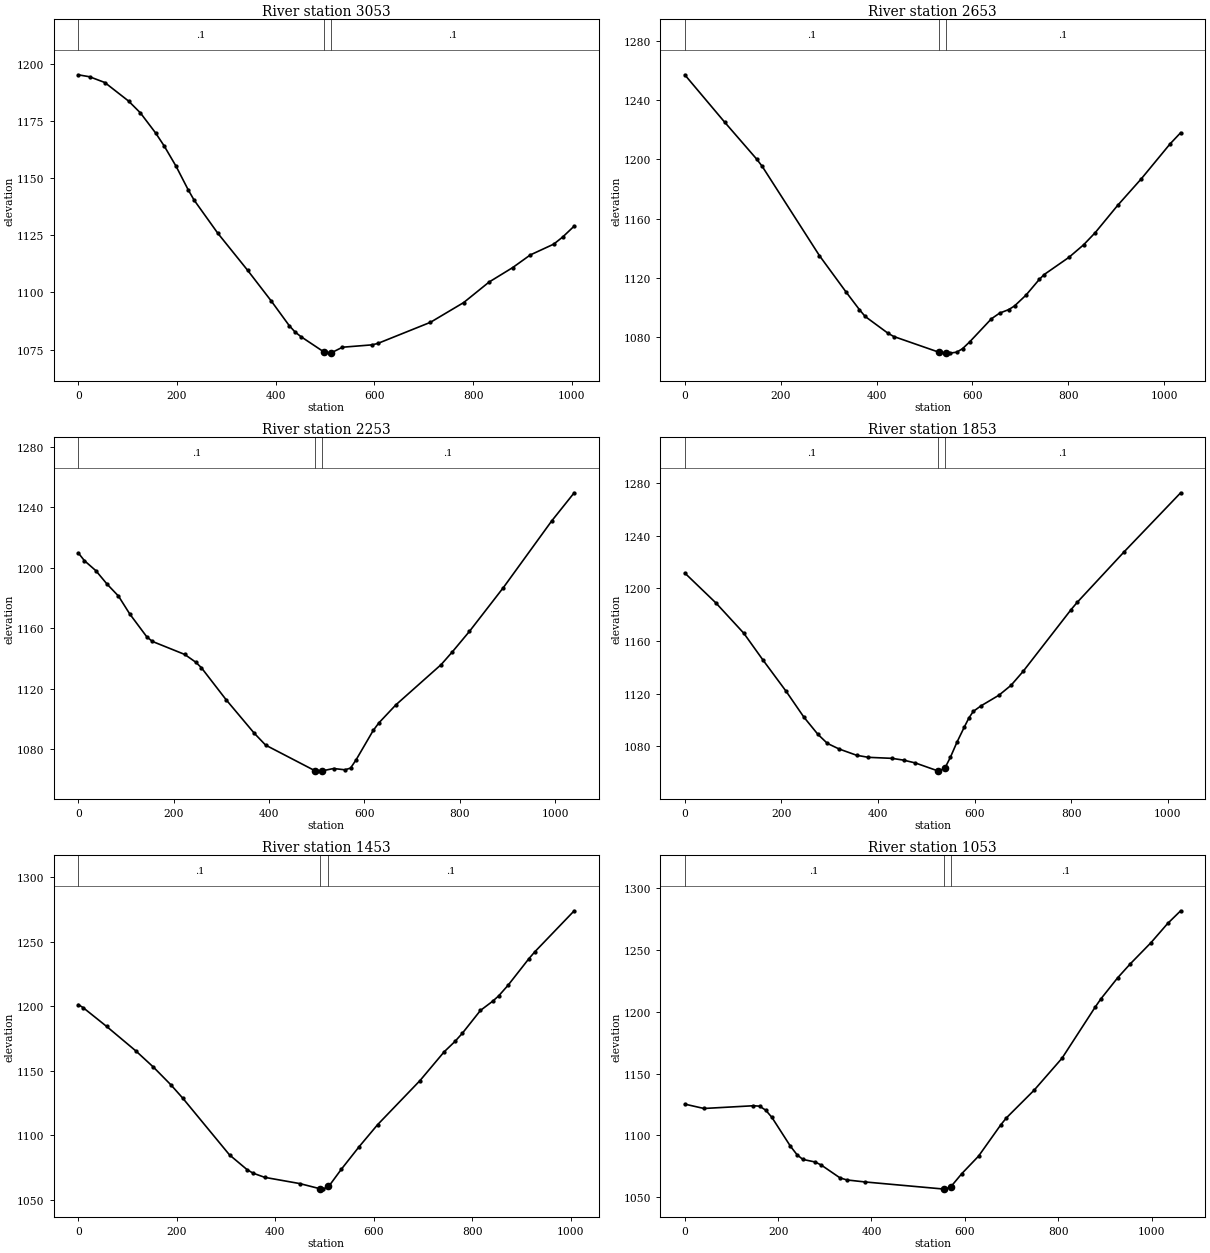
Type RM Length L Ch R = 1 ,3053,401.595,400,401.462
XS GIS Cut Line= 3
     1666034.011      283209.942     1666119.606      282712.506
     1666145.845      282213.445
#Sta/Elev= 30
       0 1195.15    22.9 1194.30    53.6 1191.79   101.8 1183.68   125.6 1178.54
   156.5 1169.75   174.1 1164.00   198.2 1155.10   222.3 1144.99   234.3 1140.46
   282.5 1125.91   342.8 1109.74   391.0 1096.23   427.1 1085.55   439.1 1082.71
   451.2 1080.66   497.2 1074.04   511.3 1073.48   512.2 1073.59   535.1 1076.06
   594.6 1077.09   606.4 1077.69   713.4 1086.96   780.7 1095.59   832.3 1104.58
   879.9 1110.87   915.6 1116.40   963.1 1121.13   981.5 1124.29  1004.5 1129.00
#Mann= 3 , 0 , 0
       0     0.1       0   497.2   0.045       0   512.2     0.1       0
Bank Sta=   497.2,   512.2
Exp/Cntr=0.3,0.1

Type RM Length L Ch R = 1 ,2653,402.005,400,398.692
XS GIS Cut Line= 3
     1666443.738      283246.836     1666493.872      282712.258
     1666573.664      282221.227
#Sta/Elev= 30
       0 1257.00    82.9 1225.14   149.8 1200.16   161.6 1195.16   280.9 1134.93
   336.0 1110.57   364.4 1098.44   376.3 1093.87   424.0 1082.52   436.0 1080.33
   529.4 1069.82   544.4 1069.25   553.2 1069.12   567.4 1069.78   579.4 1072.12
   594.6 1076.80   639.6 1092.29   656.7 1096.11   675.7 1098.50   687.9 1100.97
   711.7 1108.24   739.4 1118.83   749.8 1122.19   801.5 1133.81   832.0 1142.25
   856.1 1150.41   903.1 1168.90   952.3 1186.78  1012.4 1210.38  1034.4 1217.90
#Mann= 3 , 0 , 0
       0     0.1       0   529.4   0.045       0   544.4     0.1       0
Bank Sta=   529.4,   544.4
Exp/Cntr=0.3,0.1

Type RM Length L Ch R = 1 ,2253,389.821,400,378.665
XS GIS Cut Line= 3
     1666863.900      283348.103     1666852.750      282845.237
     1666870.067      282308.336
#Sta/Elev= 30
       0 1209.79    12.9 1204.66    36.7 1198.11    60.4 1189.15    84.2 1181.28
   107.9 1169.43   143.6 1154.31   155.4 1151.25   223.3 1142.63   246.5 1137.48
   258.1 1133.89   309.8 1112.77   369.2 1090.46   392.9 1082.64   495.5 1065.83
   499.8 1065.42   510.5 1065.52   535.5 1067.15   559.2 1066.30   571.1 1067.43
   583.0 1073.05   618.6 1092.32   630.5 1097.34   666.1 1109.26   761.2 1135.94
   784.4 1144.26   820.6 1157.94   891.8 1186.94   993.0 1230.97  1040.2 1249.61
#Mann= 3 , 0 , 0
       0     0.1       0   495.5   0.045       0   510.5     0.1       0
Bank Sta=   495.5,   510.5
Exp/Cntr=0.3,0.1

Type RM Length L Ch R = 1 ,1853,403.594,400,399.036
XS GIS Cut Line= 3
     1667076.529      283350.392     1667190.175      282831.372
     1667338.739      282359.127
#Sta/Elev= 30
       0 1211.71    64.2 1189.06   122.1 1165.98   161.4 1145.82   210.0 1121.72
   246.5 1102.23   275.5 1089.17   295.1 1082.28   319.4 1078.02   355.9 1073.22
   380.2 1071.68   428.8 1070.91   453.1 1069.54   477.4 1067.39   523.8 1061.39
   526.0 1061.20   538.8 1063.75   549.9 1071.79   563.3 1083.10   578.3 1094.46
   588.1 1101.59   597.2 1106.57   613.0 1110.75   650.4 1118.90   675.3 1126.38
   700.2 1136.90   799.7 1183.94   812.2 1189.39   909.6 1227.87  1026.4 1272.63
#Mann= 3 , 0 , 0
       0     0.1       0   523.8   0.045       0   538.8     0.1       0
Bank Sta=   523.8,   538.8
Exp/Cntr=0.3,0.1

Type RM Length L Ch R = 1 ,1453,390.52,400,396.019
XS GIS Cut Line= 3
     1667516.679      283499.186     1667544.700      283000.724
     1667675.019      282510.149
#Sta/Elev= 30
       0 1201.25     9.7 1198.93    57.2 1184.41   116.7 1165.36   152.4 1152.80
   188.1 1138.96   211.8 1128.80   307.0 1084.66   342.6 1073.26   354.5 1070.56
   378.3 1067.27   449.7 1062.42   491.7 1058.32   497.2 1058.12   506.7 1060.17
   509.4 1060.74   534.0 1073.52   570.0 1090.96   607.7 1108.13   693.7 1142.30
   742.9 1164.66   764.8 1172.69   779.7 1179.00   816.6 1196.78   841.1 1203.81
   853.4 1207.98   872.3 1216.14   914.8 1236.85   927.1 1242.30  1006.8 1274.01
#Mann= 3 , 0 , 0
       0     0.1       0   491.7   0.045       0   506.7     0.1       0
Bank Sta=   491.7,   506.7
Exp/Cntr=0.3,0.1

Type RM Length L Ch R = 1 ,1053,406.242,400,401.398
XS GIS Cut Line= 3
     1667692.856      283550.034     1667941.783      283046.269
     1667984.488      282547.594
#Sta/Elev= 30
       0 1125.34    41.0 1121.82   147.0 1124.03   160.2 1123.69   173.4 1120.45
   186.7 1114.59   226.4 1091.28   240.6 1084.41   252.9 1080.66   279.4 1078.56
   292.6 1076.05   332.4 1065.78   347.0 1064.09   385.3 1062.48   554.4 1056.72
   557.5 1056.65   569.4 1058.29   593.7 1069.24   629.4 1083.31   677.1 1108.62
   689.0 1114.20   748.6 1136.64   808.2 1162.40   879.7 1203.96   891.6 1210.41
   927.3 1227.34   954.3 1238.60   998.8 1255.78  1034.6 1271.31  1062.4 1281.54
#Mann= 3 , 0 , 0
       0     0.1       0   554.4   0.045       0   569.4     0.1       0
Bank Sta=   554.4,   569.4
Exp/Cntr=0.3,0.1

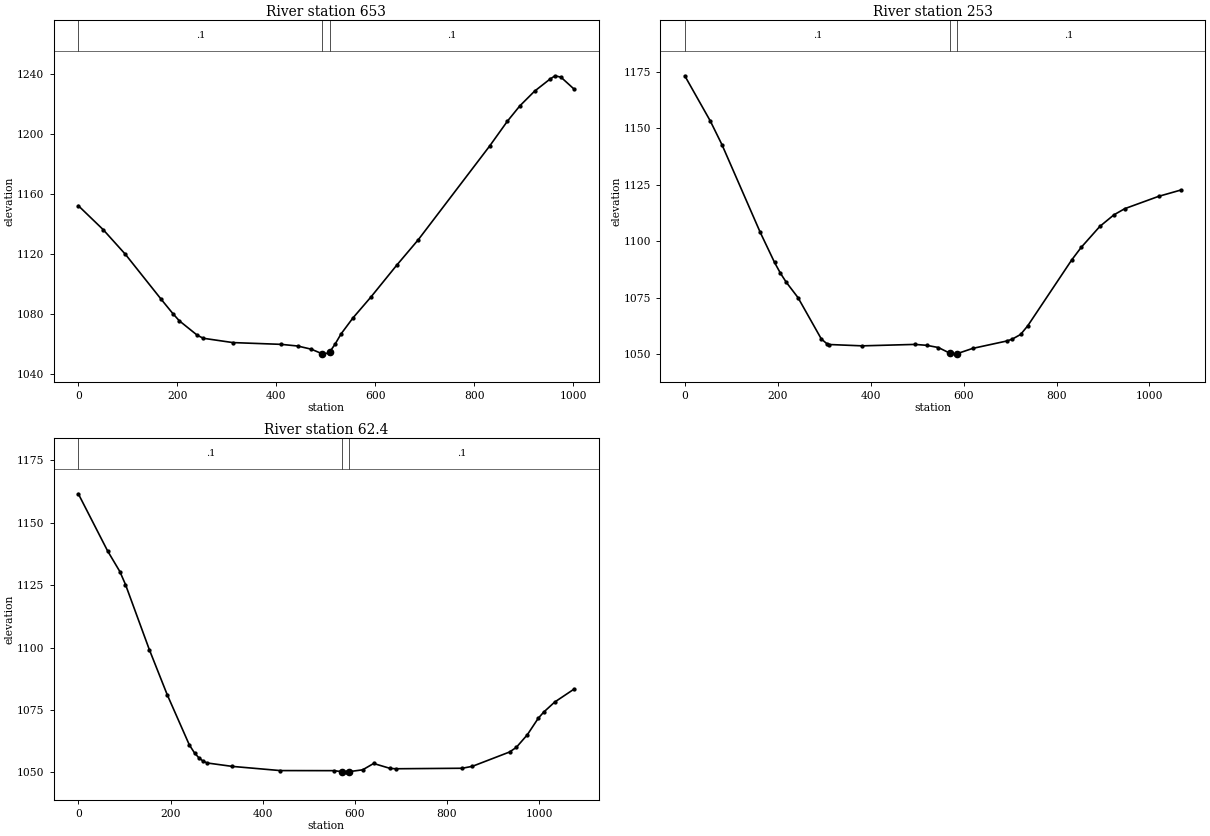
Type RM Length L Ch R = 1 ,653,396.326,400,400.649
XS GIS Cut Line= 3
     1668238.007      283594.559     1668337.350      283104.167
     1668411.057      282608.282
#Sta/Elev= 30
       0 1152.06    50.2 1136.07    95.1 1119.59   167.7 1089.43   191.2 1079.92
   204.1 1075.17   240.4 1065.53   252.5 1063.53   312.1 1060.65   410.0 1059.46
   443.0 1058.36   470.6 1056.24   492.9 1053.14   494.8 1052.94   506.9 1053.94
   507.9 1054.39   518.9 1059.71   530.9 1066.50   554.9 1077.15   590.9 1090.99
   643.1 1112.27   686.9 1129.38   831.0 1191.92   867.0 1208.56   891.9 1218.69
   921.6 1228.49   952.9 1236.60   963.0 1238.78   975.0 1237.88  1001.7 1229.87
#Mann= 3 , 0 , 0
       0     0.1       0   492.9   0.045       0   507.9     0.1       0
Bank Sta=   492.9,   507.9
Exp/Cntr=0.3,0.1

Type RM Length L Ch R = 1 ,253,189.852,190.632,191.362
XS GIS Cut Line= 3
     1668523.637      283695.587     1668715.306      283149.718
     1668813.866      282671.252
#Sta/Elev= 30
       0 1173.26    54.8 1153.31    80.0 1142.79   162.4 1104.00   193.2 1090.69
   205.8 1085.95   218.2 1082.00   243.6 1075.16   293.9 1056.83   306.5 1054.63
   311.4 1054.40   382.0 1053.81   495.2 1054.45   520.4 1054.05   545.6 1053.08
     571 1050.51   583.1 1050.15     586 1050.35   619.5 1052.68   692.4 1055.93
   704.4 1056.75   722.7 1058.85   738.0 1062.66   833.0 1091.90   853.1 1097.37
   893.3 1106.66   923.4 1111.74   946.8 1114.49  1019.5 1119.93  1067.1 1122.71
#Mann= 3 , 0 , 0
       0     0.1       0     571   0.045       0     586     0.1       0
Bank Sta=     571,     586
Exp/Cntr=0.3,0.1

Type RM Length L Ch R = 1 ,62.4,36.733,62.387,90.895
XS GIS Cut Line= 3
     1668631.594      283773.562     1668865.029      283228.144
     1668900.144      282746.892
#Sta/Elev= 30
       0 1161.63    63.6 1138.72    90.1 1130.49   102.3 1125.30   154.0 1099.24
   192.7 1081.22   240.9 1061.02   252.4 1057.75   261.4 1055.91   270.2 1054.61
   279.5 1053.81   333.8 1052.44   438.1 1050.76   554.3 1050.73   573.1 1050.31
   580.2 1050.14   588.1 1050.35   616.9 1051.06   640.7 1053.60   676.4 1051.64
   688.3 1051.49   832.9 1051.69   855.0 1052.47   935.6 1058.20   950.2 1060.04
   974.0 1065.06   997.8 1071.69  1009.7 1074.18  1033.5 1078.20  1075.8 1083.43
#Mann= 3 , 0 , 0
       0     0.1       0   573.1   0.045       0   588.1     0.1       0
Bank Sta=   573.1,   588.1
Exp/Cntr=0.3,0.1